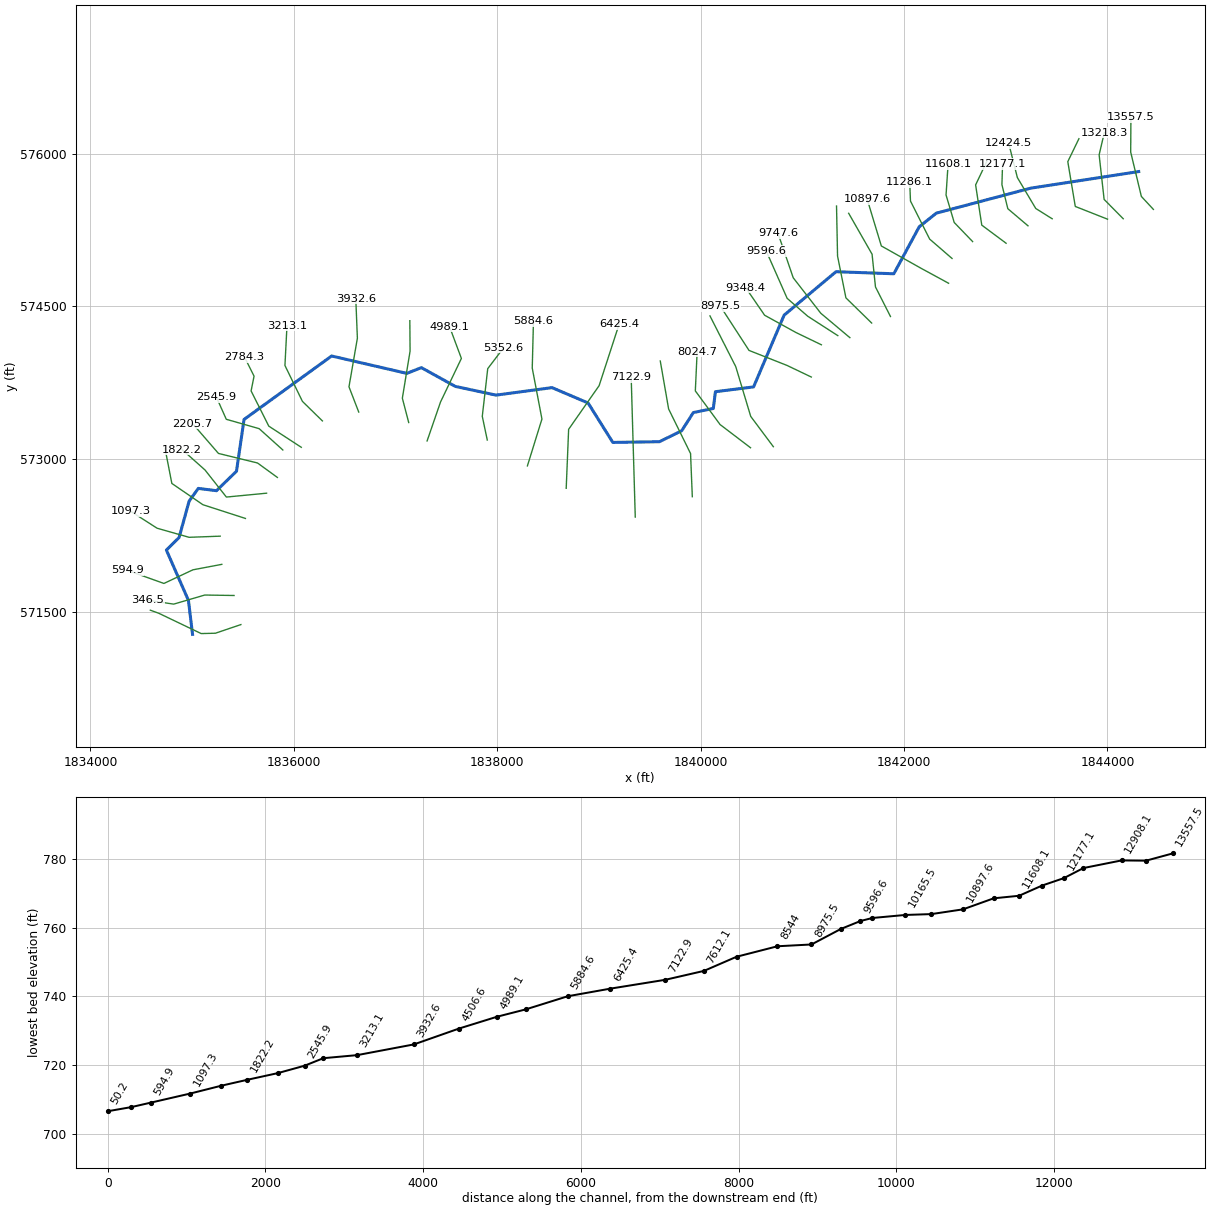
--- NP20.prj (project) ---

Proj Title=NP20
Current Plan=p01
Default Exp/Contr=0,0
English Units
Geom File=g01
Flow File=f01
Plan File=p01
BEGIN DESCRIPTION:
AMEC Environment & Infrastructure, 2013
Projection: NAD 1983 State Plane West Virginia South FIPS 4702 (US Feet)
Vertical Datum: NAVD 1988
END DESCRIPTION:
DSS Export Rating Curves= 0
DSS Export Rating Curve Sorted= 0
DSS Export Volume Flow Curves= 0
DXF OffsetX= 0
DXF OffsetY= 0
DXF ScaleX= 0
DXF ScaleY= 0

--- NP20.p01 (plan) ---

Plan Title=Floodplain
Program Version=4.00
Geom File=g01
Flow File=f01
K Sum by GR=0
Std Step Tol=0.01
Critical Tol=0.01
Num of Std Step Trials=20
Max Error Tol=0.3
Flow Tol Ratio=0.001
Split Flow NTrial=30
Split Flow Tol=0.02
Split Flow Ratio=0.02
Log Output Level=0
Friction Slope Method=1
Unsteady Friction Slope Method=2
Unsteady Bridges Friction Slope Method=1
Global Log Level=0
CheckData=False
Run HTab=0
Run UNet=0
Run PostProcess=0
UNET Theta=0
UNET Theta Warmup=0
UNET ZTol=0
UNET ZSATol=0
UNET MxIter=0
UNET MaxInSteps=0
UNET DtIC=0
UNET DtMin=0
UNET MaxCRTS=0
UNET WFStab=0
UNET SFStab=0
UNET WFX=0
UNET SFX=0
UNET DSS MLevel=0
UNET DZMax Abort=0
UNET Convert EG Bridges=0
UNET Use Existing IB Tables=0
UNET Froude Limit=0
UNET Froude Power=0
Write IC File=0
Echo Input=False
Echo Output=False
Write Detailed=0

--- NP20.f01 (steady flow) ---

Flow Title=NFF Regression Equation
Program Version=4.00
Number of Profiles=1
Profile Names=P100yr
River Rch & RM=NP20,Main      ,13557.5
911.4881
River Rch & RM=NP20,Main      ,11900.7
957.6988
River Rch & RM=NP20,Main      ,10897.6
1063.996
River Rch & RM=NP20,Main      ,9747.6
1126.822
River Rch & RM=NP20,Main      ,7612.1
1235.914
River Rch & RM=NP20,Main      ,4506.6
1363.389
River Rch & RM=NP20,Main      ,346.5
1504.918
Boundary for River Rch & Prof#=NP20,Main      ,1
Up Type=0
Dn Type=3
Dn Slope=0.004852

--- NP20.g01 (geometry) ---

Geom Title=USGS 3m DEM
Program Version=4.10

River Reach=NP20            ,Main
Reach XY= 30
     1844308.136      575822.963     1843244.253      575659.481
      1842318.61       575414.57     1842150.156      575280.838
     1841900.093      574818.869     1841331.528      574839.082
     1840821.628       574412.44     1840521.211      573707.334
      1840146.09      573660.427     1840125.256      573495.441
     1839929.013       573455.49     1839814.399      573276.606
     1839595.581      573168.923     1839137.097      573161.957
     1838893.945      573549.227     1838539.656      573700.303
     1837987.928      573626.671     1837587.952       573712.42
     1837254.267      573896.861     1837111.732      573840.264
     1836372.262      574011.077     1835510.895      573387.571
     1835436.643      572879.022     1835240.002      572687.676
     1835061.123      572710.245     1834970.821      572585.201
      1834872.25      572227.743     1834747.214      572104.433
      1834964.32      571609.488     1835004.459      571276.255

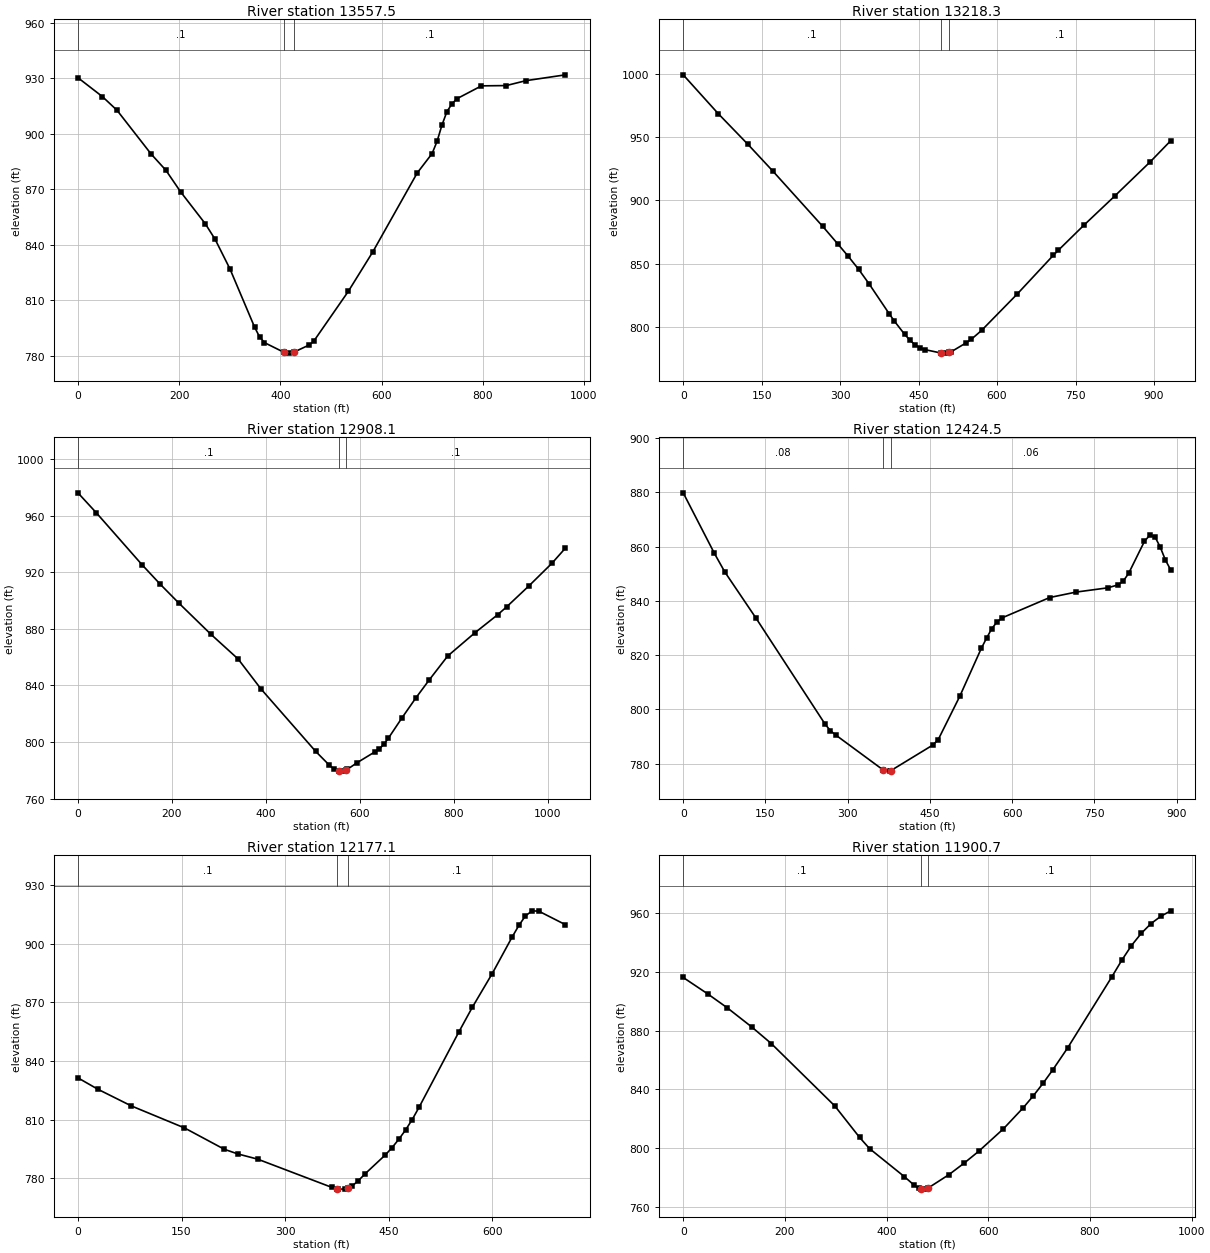
Type RM Length L Ch R = 1 ,13557.5 ,341.9,339.2,336.3
XS GIS Cut Line= 4
     1844452.636      575451.222     1844334.285      575578.505
     1844229.333      576013.947     1844231.566      576355.602
#Sta/Elev= 30
       0  930.39    48.3  920.19    77.2   912.8   144.8  889.09   173.8  880.38
     203  868.68   251.7  851.45   271.2  842.99   300.4  827.06   349.1  795.58
   358.8  790.39   368.6  787.21   407.5  781.93   417.2  781.54     427  782.11
   456.2  785.84   465.9  787.95   534.1  814.85   582.8  836.32   670.5  878.94
   699.8  889.38   709.6  895.96   719.3  904.77   729.1  912.04   738.9  916.18
   748.6  918.99   797.4  925.98   846.2  926.13   885.3  928.79   963.4  931.94
#Mann= 3 , 0 , 0
       0      .1       0   407.5    .045       0     427      .1       0
Bank Sta=407.5,427
XS Rating Curve= 0 ,0
Exp/Cntr=0.3,0.1

Type RM Length L Ch R = 1 ,13218.3 ,308.7,310.2,311.2
XS GIS Cut Line= 4
     1844155.642      575359.668     1843968.067      575549.476
     1843918.941      575987.151       1843970.3      576205.988
#Sta/Elev= 30
       0  998.97    66.7  968.46   123.9  944.05   171.6  922.92   266.8  879.38
   296.2  865.24   315.8  855.68   335.4  845.53   354.9  834.35   394.1  810.32
   403.9  804.58   423.4  794.22   433.2  789.78     443  786.03   452.8  783.54
   462.6  782.15     492  779.59   501.8  779.43  508.61780.0421   511.5   780.3
   540.9  787.53   550.7  790.31   570.3  797.29   638.8  826.15   707.3  856.49
     717  860.51   765.9  880.29   824.6   903.2     893   930.4   932.1  947.03
#Mann= 3 , 0 , 0
       0      .1       0     492    .045       0  508.61      .1       0
Bank Sta=492,508.61
XS Rating Curve= 0 ,0
Exp/Cntr=0.3,0.1

Type RM Length L Ch R = 1 ,12908.1 ,476.1,483.6,491.3
XS GIS Cut Line= 4
     1844001.563      575355.202     1843684.472      575480.252
     1843610.782       575920.16       1843720.2      576145.696
#Sta/Elev= 30
       0  976.03      39  961.99   136.3   925.3   175.3  911.44   214.2  898.36
   282.4  876.32   340.9  858.69   389.3  837.64   505.7  793.53   534.8  783.79
   544.5   781.1   555.2  779.56   563.9   779.5   570.2  780.34   573.6  780.79
     593  785.22   631.8  793.06   641.4  795.24   651.1  798.42   660.8   802.8
   689.9  817.25     719  831.11   748.1  844.11   786.9  860.77   844.7  877.16
     893  889.88   912.2  895.44   960.4   910.5  1008.6  926.22  1037.6  937.05
#Mann= 3 , 0 , 0
       0      .1       0   555.2    .045       0   570.2      .1       0
Bank Sta=555.2,570.2
XS Rating Curve= 0 ,0
Exp/Cntr=0.3,0.1

Type RM Length L Ch R = 1 ,12424.5 ,253.2,247.4,241.6
XS GIS Cut Line= 4
       1843457.1      575359.368     1843295.924      575460.155
     1843115.048      575763.847     1843030.192      576098.803
#Sta/Elev= 30
       0  879.82      57  857.47      76  850.63   133.1  833.55   258.8  794.58
   268.6  792.15   278.5  790.54   363.6  777.88   376.6  777.29   378.6  777.47
   455.2   786.9     465  788.89   504.3  804.84   543.6  822.52   553.2  826.28
   562.8  829.81   572.4  832.28     582   833.8   668.4  841.25   716.3  843.25
   773.9  844.81   793.1  845.91   802.7  847.38   812.3  850.15   841.1  861.94
   850.7  864.18   860.3  863.61   869.9  859.82   879.5  854.99   889.1  851.39
#Mann= 3 , 0 , 0
       0     .08       0   363.6    .045       0   378.6     .06       0
Bank Sta=363.6,378.6
XS Rating Curve= 0 ,0
Exp/Cntr=0.3,0.1

Type RM Length L Ch R = 1 ,12177.1 ,278.4,276.4,274.4
XS GIS Cut Line= 4
     1843219.443      575290.027     1843020.982      575458.342
     1842963.203      575694.486     1842969.483      575896.715
#Sta/Elev= 30
       0  831.36    28.9  825.52    77.1  817.02   154.2  805.72     212  794.76
   231.3  792.41   260.2  789.72   367.2  775.31   375.6   774.5   376.9  774.37
   386.6  774.39   390.6  774.98   396.4  775.83   406.1  778.76   415.8  782.26
     445   791.9   454.7  795.63   464.4  799.87   474.2  804.64   483.9  810.02
   493.6  816.18   551.5  854.95   570.8  867.46   599.7  884.78   628.6  903.55
   638.2   909.4   647.8  914.33   657.5   916.9   667.1  916.72   705.7  909.79
#Mann= 3 , 0 , 0
       0      .1       0   375.6    .045       0   390.6      .1       0
Bank Sta=375.6,390.6
XS Rating Curve= 0 ,0
Exp/Cntr=0.3,0.1

Type RM Length L Ch R = 1 ,11900.7 ,289.5,292.7,295.8
XS GIS Cut Line= 4
      1843004.14      575118.872     1842764.859      575296.843
     1842704.567       575692.09     1842816.779      575927.549
#Sta/Elev= 30
       0  916.05    48.1  904.93    86.6  895.45   134.7  882.44   173.2  871.16
   298.2  828.73     347  807.32   366.5  799.74   434.7  780.77   454.2  774.91
     464  772.66   467.4   772.5   473.7  772.21   482.4  773.11   522.5  782.02
   551.8  789.68     581  797.87   629.8   813.2   668.8  827.53   688.3  835.51
   707.7  844.12     727  853.35     756  868.14   842.9  916.41   862.3  927.61
   881.6  937.74   900.9  946.06   920.2  952.71   939.5  957.67   958.9  961.35
#Mann= 3 , 0 , 0
       0      .1       0   467.4    .045       0   482.4      .1       0
Bank Sta=467.4,482.4
XS Rating Curve= 0 ,0
Exp/Cntr=0.3,0.1

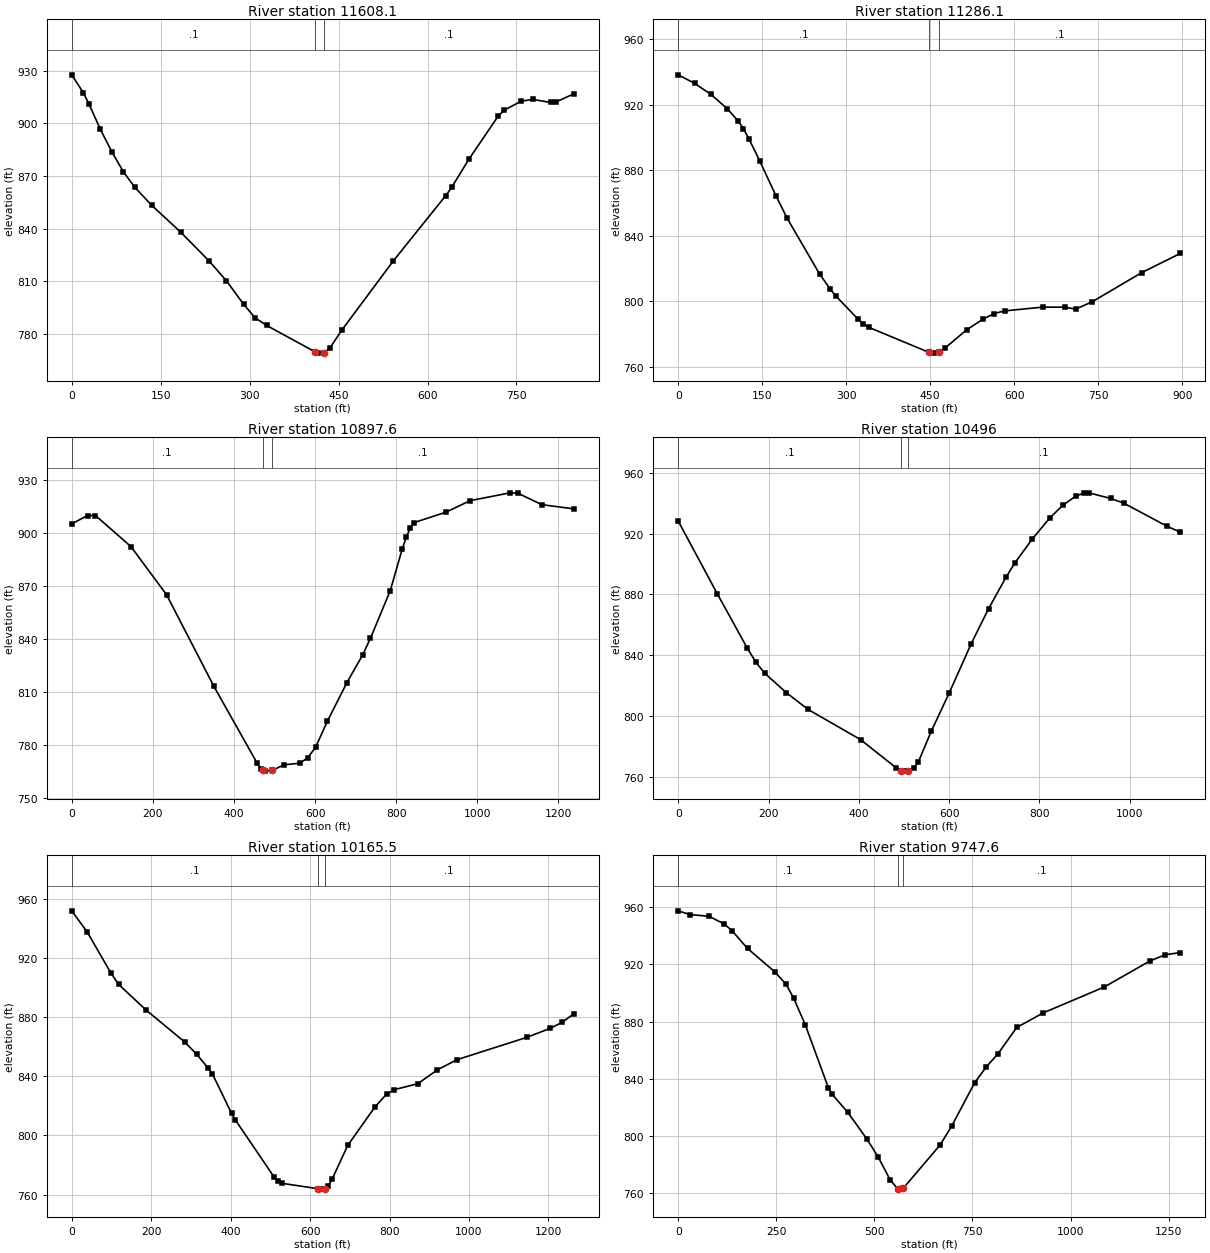
Type RM Length L Ch R = 1 ,11608.1 ,317.9,322,325.9
XS GIS Cut Line= 4
     1842674.984      575135.098     1842494.108      575322.673
     1842413.719      575592.871     1842433.816      575896.564
#Sta/Elev= 30
       0  927.56    19.3  917.45      29  910.99    48.3  896.49    67.6  883.79
    86.9   872.5   106.2   863.6   135.1  853.24   183.4  838.16   231.6  821.65
   260.6  810.51   289.7  797.09   309.2  789.33   328.6     785     410  770.01
   416.1  769.24   425.8  769.56   435.6  772.27     455  782.12   542.5  821.78
   630.8  858.88   640.7  863.51   670.1  879.71   719.2  904.07     729  907.38
   758.5  912.65   778.1  913.54   807.6  911.84   817.4  912.26   846.8  916.74
#Mann= 3 , 0 , 0
       0      .1       0     410    .045       0   425.8      .1       0
Bank Sta=410,425.8
XS Rating Curve= 0 ,0
Exp/Cntr=0.3,0.1

Type RM Length L Ch R = 1 ,11286.1 ,375.1,388.5,402.1
XS GIS Cut Line= 4
     1842472.678      574969.259     1842252.352      575159.811
     1842063.992      575533.377     1842056.433      575720.154
#Sta/Elev= 30
       0  938.25    29.1  933.07    58.3  926.34    87.4   917.6   106.8   910.2
   116.5  905.33   126.2  899.23   145.6   885.7   174.8  864.28   194.2  850.96
   252.5  816.71   271.9  807.33   281.6   803.3   320.5  789.43   330.2  786.43
   339.9  784.29     447  769.08   456.7   768.5   466.4  769.26   476.2  771.53
   515.1  782.73   544.3   789.2   563.7  792.62   583.2  794.27   651.3  796.57
   690.2  796.53   709.7  795.36   739.2  799.82   827.7  817.61   896.6  829.31
#Mann= 3 , 0 , 0
       0      .1       0     447    .045       0   466.4      .1       0
Bank Sta=447,466.4
XS Rating Curve= 0 ,0
Exp/Cntr=0.3,0.1

Type RM Length L Ch R = 1 ,10897.6 ,423.6,401.6,379
XS GIS Cut Line= 4
     1842438.438      574725.858     1842164.519      574874.727
     1841777.459      575092.076     1841637.523       575553.57
#Sta/Elev= 30
       0  905.19      39  909.92    58.4  909.92   146.1  892.28   233.8  865.06
   350.4  813.26   456.5  770.05   466.2  766.23  470.82765.7824   475.8   765.3
   493.1  765.69   524.1  768.87   562.7  769.81     582  772.91   601.3  778.87
   630.2  793.55   678.5  815.44   717.1  830.99   736.4  840.44   785.2  867.39
   814.7  890.89   824.6   897.5   834.4  902.76   844.2  905.92     923  911.84
     982   918.3  1080.4  922.75  1100.1  922.51  1159.2  916.04  1237.9  913.68
#Mann= 3 , 0 , 0
       0      .1       0  470.82    .045       0   493.1      .1       0
Bank Sta=470.82,493.1
XS Rating Curve= 0 ,0
Exp/Cntr=0.3,0.1

Type RM Length L Ch R = 1 ,10496   ,328.2,330.4,332.3
XS GIS Cut Line= 4
     1841867.179      574399.163     1841719.799      574689.457
     1841686.303      575011.015       1841456.3      575412.961
#Sta/Elev= 30
       0  928.25    86.2  880.64   153.2  844.58   172.4  835.32   191.5  828.23
   239.4   815.5   287.3   804.5   403.9   784.6   482.3  766.18   493.6  764.28
   501.9  763.92   508.6  764.28   521.5   765.9   531.3   769.6   560.7  790.32
   599.9  815.12   648.9  847.68   687.4  870.72     726  891.35   745.3  900.63
   783.9  916.35   822.5  930.17   851.5  938.54   880.4  944.65   899.7  946.78
   909.4  946.81   957.6  943.13   986.5  940.06    1083  924.79    1112  920.94
#Mann= 3 , 0 , 0
       0      .1       0   493.6    .045       0   508.6      .1       0
Bank Sta=493.6,508.6
XS Rating Curve= 0 ,0
Exp/Cntr=0.3,0.1

Type RM Length L Ch R = 1 ,10165.5 ,407.4,417.9,428.4
XS GIS Cut Line= 4
     1841682.183      574335.077     1841429.106      574582.199
     1841346.882       574993.15     1841336.807      575484.346
#Sta/Elev= 30
       0  952.05    39.3  937.51    98.3  910.05   117.9  902.26   186.7  884.99
   284.9  863.12   314.4  855.02   343.9  845.42   353.7  841.89   402.4  814.89
   412.2  810.38   509.7  771.73   519.4  768.99   529.2   767.6   619.4  763.98
   626.6  763.67   636.4  763.86   646.1  765.89   655.9  770.69   694.8  793.27
   763.1  819.22   792.5  827.94   812.1  831.01   871.1     835   920.2  844.35
   969.3  851.23  1146.2  866.45  1205.2  872.57  1234.6  876.58  1264.1  882.36
#Mann= 3 , 0 , 0
       0      .1       0   619.4    .045       0   636.4      .1       0
Bank Sta=619.4,636.4
XS Rating Curve= 0 ,0
Exp/Cntr=0.3,0.1

Type RM Length L Ch R = 1 ,9747.6  ,146.6,151,155.4
XS GIS Cut Line= 4
     1841467.906      574191.375     1841181.983      574431.097
     1840911.042      574779.451     1840760.081      575219.724
#Sta/Elev= 30
       0   957.5    29.5   954.9    78.6  953.67   117.8  948.22   137.5  943.47
   176.7  931.16   245.5  914.99   274.9  906.16   294.6  896.21     324  877.65
   382.9  833.57   392.7  829.02     432  816.59     481   797.8   510.4  784.96
   539.8  769.44   559.4  763.02   569.3  762.79  574.22763.5874   667.3  793.59
   696.8  806.78   755.6  837.22     785  848.22   814.4  857.24   862.9  875.88
   930.8  886.14  1085.9  904.18  1202.3  922.41  1241.1  926.76  1279.9  928.29
#Mann= 3 , 0 , 0
       0      .1       0   559.4    .045       0  574.22      .1       0
Bank Sta=559.4,574.22
XS Rating Curve= 0 ,0
Exp/Cntr=0.3,0.1

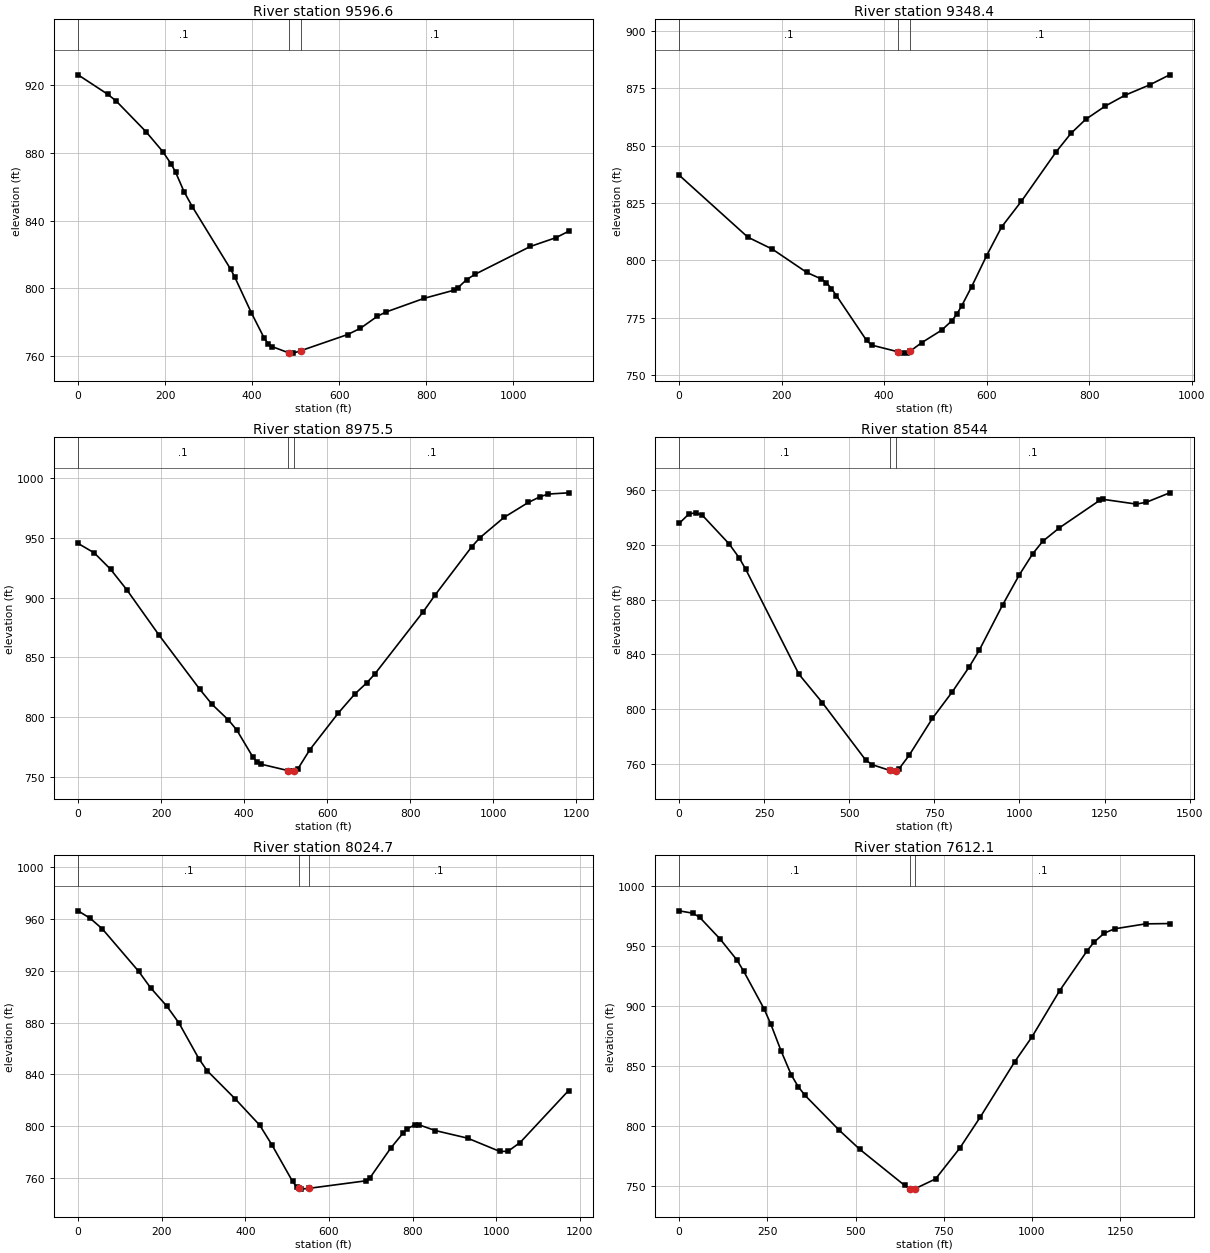
Type RM Length L Ch R = 1 ,9596.6  ,243,248.2,252.9
XS GIS Cut Line= 4
     1841349.276      574211.261     1841054.515      574401.069
     1840851.309      574577.479      1840645.87      575041.951
#Sta/Elev= 30
       0  925.79    68.2  914.33    87.6  910.37   155.8  892.39   194.8  880.57
   214.2  873.17     224  868.57   243.5  857.04   262.9  848.01   350.6  811.39
   360.2  806.68   398.6  785.52   427.5  770.95   437.1  767.34   446.7  765.68
   485.1     762   494.8  761.91   512.6  763.39   619.7  772.86     649  776.53
     688  783.62   707.6   786.1   795.5  794.18   863.9  798.95   873.6  800.52
   893.2   805.2   912.7  808.36  1039.7  824.72  1098.3  829.88  1127.6  833.66
#Mann= 3 , 0 , 0
       0      .1       0   485.1    .045       0   512.6      .1       0
Bank Sta=485.1,512.6
XS Rating Curve= 0 ,0
Exp/Cntr=0.3,0.1

Type RM Length L Ch R = 1 ,9348.4  ,369.3,372.8,375.7
XS GIS Cut Line= 4
     1841187.782        574121.3     1840937.682      574241.884
     1840629.523      574411.595     1840444.181      574681.792
#Sta/Elev= 30
       0  837.15     134  810.14   181.9  804.91   248.9  794.78   277.6   791.9
   287.4  790.29   297.2  787.71     307  784.63   365.6  765.18   375.4  763.12
   427.3  760.18     434  759.66   443.8  759.61  450.18760.3587   473.1  764.14
   512.2  769.61   531.7  773.62   541.5  776.48   551.3   780.2   570.8  788.59
   600.1  802.14   629.4  814.64     668  825.84   735.5  847.28   764.4  855.33
   793.3  861.47   831.8  867.29   870.4  872.01   918.6  876.53   957.1  880.86
#Mann= 3 , 0 , 0
       0      .1       0   427.3    .045       0  450.18      .1       0
Bank Sta=427.3,450.18
XS Rating Curve= 0 ,0
Exp/Cntr=0.3,0.1

Type RM Length L Ch R = 1 ,8975.5  ,452,431.6,410.9
XS GIS Cut Line= 4
      1841088.94      573804.359     1840850.594      573918.094
     1840476.298      574065.884     1840195.726      574498.088
#Sta/Elev= 30
       0  945.28    39.1  937.32    78.2  923.72   117.4  906.55   195.6  868.43
   293.5  823.33     323  810.77   362.2  797.83   381.9  789.68   421.1  766.89
     431  762.81   440.8  760.91   505.7  755.56   519.3   755.1   520.7  755.33
   529.1  756.74   558.5  773.04   627.2  803.73   666.5  819.42   695.7  828.91
   715.1  836.31   831.8  888.33     861  902.59   948.5  942.51   967.9  949.96
  1026.2  966.99  1084.6  979.45  1113.7  984.36  1133.2   986.5  1181.8  987.52
#Mann= 3 , 0 , 0
       0      .1       0   505.7    .045       0   520.7      .1       0
Bank Sta=505.7,520.7
XS Rating Curve= 0 ,0
Exp/Cntr=0.3,0.1

Type RM Length L Ch R = 1 ,8544    ,511,519.3,527.1
XS GIS Cut Line= 4
     1840715.313      573120.125     1840493.002      573417.863
     1840346.118      573906.153     1840092.322      574405.058
#Sta/Elev= 30
       0  935.86    29.3  942.91    48.9  943.55    68.4   941.8   146.7  920.91
     176  910.86   195.6  902.33     352  825.47   420.6  804.74   548.1  762.68
   567.7  759.24   619.2  755.09   626.5  754.58   636.3  754.63   646.1  756.25
   675.6  766.09   744.2  793.21     803  812.75   852.1   830.8   881.5  842.93
   950.2  876.11   999.3  898.13  1038.6  913.57  1068.1  922.74  1117.2  932.64
    1235  952.64  1244.8  953.52    1343  950.02  1372.5  951.33  1441.2  958.25
#Mann= 3 , 0 , 0
       0      .1       0   619.2    .045       0   636.3      .1       0
Bank Sta=619.2,636.3
XS Rating Curve= 0 ,0
Exp/Cntr=0.3,0.1

Type RM Length L Ch R = 1 ,8024.7  ,416.4,412.6,408.8
XS GIS Cut Line= 4
     1840491.075      573109.735     1840191.848      573337.505
     1839948.447      573667.994     1839966.312      574054.309
#Sta/Elev= 30
       0  966.16    28.9   960.4    57.8  952.31   144.6  919.62   173.6  906.73
   212.1   892.7   241.1  879.74   289.3  851.89   308.6   842.9     376  821.07
   434.7  800.75     464  785.45   512.9  757.54   522.6  753.24  527.27752.4252
   532.4  751.53     552  752.13   688.8  757.96   698.6  760.48   747.4  783.02
   776.7  794.56   786.5  797.92   805.8   801.2   815.5  801.12   854.2  796.71
   931.5  790.85  1008.9  780.57  1028.2  780.73  1057.2  787.46  1173.2  827.57
#Mann= 3 , 0 , 0
       0      .1       0  527.27    .045       0     552      .1       0
Bank Sta=527.27,552
XS Rating Curve= 0 ,0
Exp/Cntr=0.3,0.1

Type RM Length L Ch R = 1 ,7612.1  ,498.8,489.2,479.3
XS GIS Cut Line= 4
     1839918.705      572628.819     1839901.495      573052.638
     1839685.786      573490.616     1839603.757      573961.731
#Sta/Elev= 30
       0  979.19    38.6  977.23    57.8  973.91   115.7  955.86   163.9  938.24
   183.2   928.8     241  897.45   260.3  884.53   289.2   862.4   318.1  842.44
   337.4  832.86   356.7  825.57   453.5  796.58     512   780.6     639  750.58
   654.5  747.81   658.5  747.43   669.5  747.88   726.9  755.93   795.2   781.4
   853.8  807.49   951.4  853.53  1000.2  874.18  1078.3  912.51  1156.4  945.81
  1175.9  953.03  1205.2   960.6  1234.4   964.2  1322.3  968.33  1390.6   968.6
#Mann= 3 , 0 , 0
       0      .1       0   654.5    .045       0   669.5      .1       0
Bank Sta=654.5,669.5
XS Rating Curve= 0 ,0
Exp/Cntr=0.3,0.1

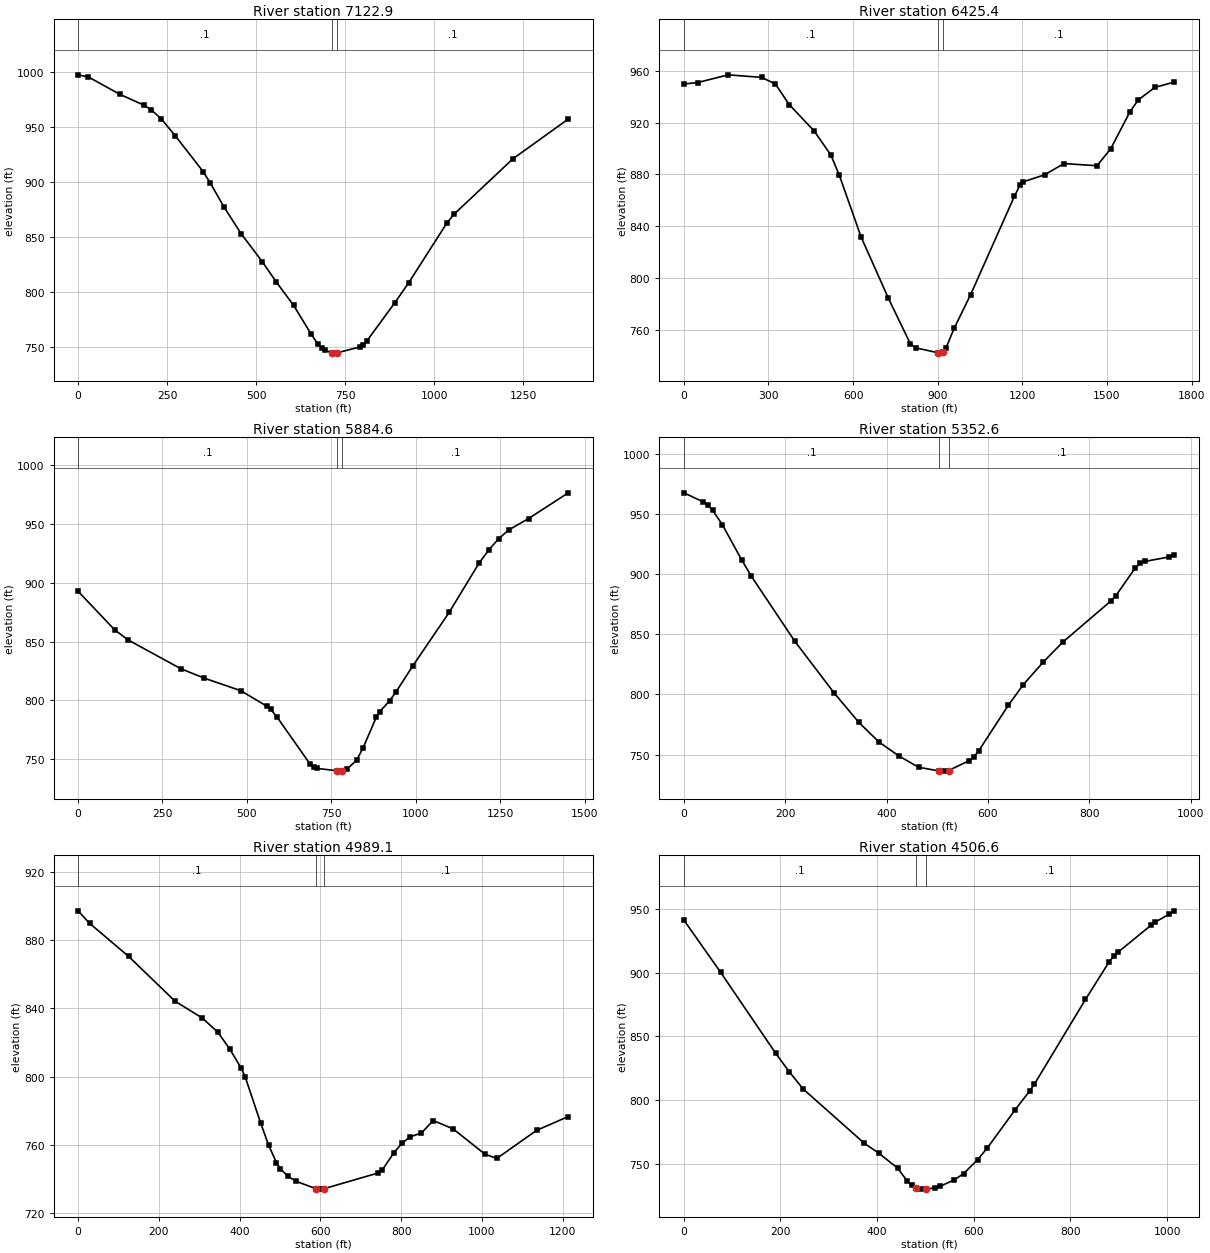
Type RM Length L Ch R = 1 ,7122.9  ,711.8,697.5,683
XS GIS Cut Line= 4
     1839357.787      572428.491     1839343.307      572925.648
      1839330.47      573366.389     1839317.721      573804.075
#Sta/Elev= 30
       0  997.56    29.3  995.58     117  979.92   185.3  969.95   204.8  965.93
   234.1  957.39   273.1  942.11   351.1  909.73   370.6  899.64   409.6  877.58
   458.4  853.04     517  827.93   556.2  809.59   605.2  788.19   654.1  762.24
   673.7  752.78   683.5  749.62   693.3  747.61   711.6  745.14   722.7  744.85
   726.6  745.08   791.3  750.48   801.1  752.48   810.9  755.99   889.3  790.65
   928.5  808.91  1035.6   863.1  1055.1  870.88  1220.5  921.24  1376.2  957.41
#Mann= 3 , 0 , 0
       0      .1       0   711.6    .045       0   726.6      .1       0
Bank Sta=711.6,726.6
XS Rating Curve= 0 ,0
Exp/Cntr=0.3,0.1

Type RM Length L Ch R = 1 ,6425.4  ,522.4,540.8,558.7
XS GIS Cut Line= 4
     1838678.784      572711.231     1838702.603      573290.828
     1839002.405      573719.709     1839198.833      574322.987
#Sta/Elev= 30
       0  949.71    49.2  950.89   157.3  956.82   275.3  954.85   324.4  949.79
   373.6  933.88   462.1  913.46   521.1  895.02   550.6  879.69   628.5   831.7
   725.4  784.42     803  749.43   822.3  746.35   899.9  742.61   909.6  742.28
   919.2  742.78   928.9  746.09     958  761.33  1016.2  787.21  1171.7  863.18
  1191.2  871.66    1201  874.18  1279.1  879.77  1347.4  888.42  1464.5  886.73
  1513.3  899.87  1581.6   928.5  1610.9  937.49  1669.5  947.11  1737.8  951.21
#Mann= 3 , 0 , 0
       0      .1       0   899.9    .045       0   919.2      .1       0
Bank Sta=899.9,919.2
XS Rating Curve= 0 ,0
Exp/Cntr=0.3,0.1

Type RM Length L Ch R = 1 ,5884.6  ,538.7,532,525
XS GIS Cut Line= 4
     1838297.183      572931.309     1838440.098      573391.811
     1838344.821      573892.011     1838356.731      574352.512
#Sta/Elev= 30
       0  892.65   108.2  859.98   147.6  851.47     305  826.84   373.9  818.93
   482.2  808.26   560.5  794.91   570.3  792.58   589.9  785.69   687.8  745.82
   697.6  743.42   707.4  742.42     768  740.32   775.9  740.07     783  740.25
   795.5  741.58   824.9  749.21   844.5  760.03   883.6  785.98   893.4  790.47
   922.8  799.76   942.4   807.6   991.4  829.29  1099.2  874.73  1187.4   916.4
  1216.8  927.85  1246.2  937.32  1275.6  944.65  1334.4  954.33    1452  976.13
#Mann= 3 , 0 , 0
       0      .1       0     768    .045       0     783      .1       0
Bank Sta=768,783
XS Rating Curve= 0 ,0
Exp/Cntr=0.3,0.1

Type RM Length L Ch R = 1 ,5352.6  ,371.3,363.5,355.5
XS GIS Cut Line= 4
      1837902.68      573185.503     1837853.554      573417.739
     1837907.146      573886.676     1838063.459      574092.116
#Sta/Elev= 30
       0  967.71      38  960.21    47.5  957.24      57  953.05      76   941.2
   113.9   912.1   132.9  898.54   218.4  844.59   296.4  801.34   345.5  776.72
   384.9  760.55   424.2   748.9   463.5  739.44   502.9  736.49   512.7  736.26
   522.5  736.77   561.9  744.76   571.7  747.86   581.5  752.88   640.5  791.14
     670  808.24   709.4  826.99   747.6  843.46   843.2  877.94   852.8  882.28
     891  905.35   900.6  909.12   910.1  910.68     958   914.4   967.5  916.22
#Mann= 3 , 0 , 0
       0      .1       0   502.9    .045       0   522.5      .1       0
Bank Sta=502.9,522.5
XS Rating Curve= 0 ,0
Exp/Cntr=0.3,0.1

Type RM Length L Ch R = 1 ,4989.1  ,475.5,482.5,489.7
XS GIS Cut Line= 4
     1837310.926      573176.571     1837442.675       573558.42
     1837648.114      573987.163     1837531.092       574300.45
#Sta/Elev= 30
       0  897.02    28.8  889.65     125  870.39   240.4  844.08   307.8  834.25
   346.2  825.94   375.1  816.32   403.9  804.95   413.6  799.97   452.4  772.61
   471.9  759.82   491.3  749.64     501  745.96   520.4  741.53   539.8  738.71
   588.3  734.46     598  734.13   607.7  734.29   743.5  743.62   753.2  745.34
   782.3  755.54   801.7  760.84   821.2  764.64   850.2     767   879.4  774.28
   928.5  769.42  1007.2  754.63  1036.7  752.07  1135.1   768.5  1213.8  776.63
#Mann= 3 , 0 , 0
       0      .1       0   588.3    .045       0   607.7      .1       0
Bank Sta=588.3,607.7
XS Rating Curve= 0 ,0
Exp/Cntr=0.3,0.1

Type RM Length L Ch R = 1 ,4506.6  ,573.5,574,572.7
XS GIS Cut Line= 4
      1837130.05      573357.447     1837067.525      573596.382
     1837143.448       574058.62     1837141.215      574357.847
#Sta/Elev= 30
       0  941.05      76  900.23     190  836.89   218.5  822.27     247  808.93
   373.8  766.43   403.1  758.91   442.2  747.17   461.7  737.39   471.4  733.64
   481.2  731.67     491   730.7   500.7  730.75   520.2  731.71     530  732.87
   559.3  737.88   578.8  742.75   608.1  753.75   627.6  762.67   686.1  792.93
   715.4  807.28   725.1  812.52   831.2  878.95   879.5  907.97   889.2  912.54
   898.8  915.94   966.4  936.84     976  939.54    1005  945.69  1014.6  948.23
#Mann= 3 , 0 , 0
       0      .1       0   481.2    .045       0   500.7      .1       0
Bank Sta=481.2,500.7
XS Rating Curve= 0 ,0
Exp/Cntr=0.3,0.1

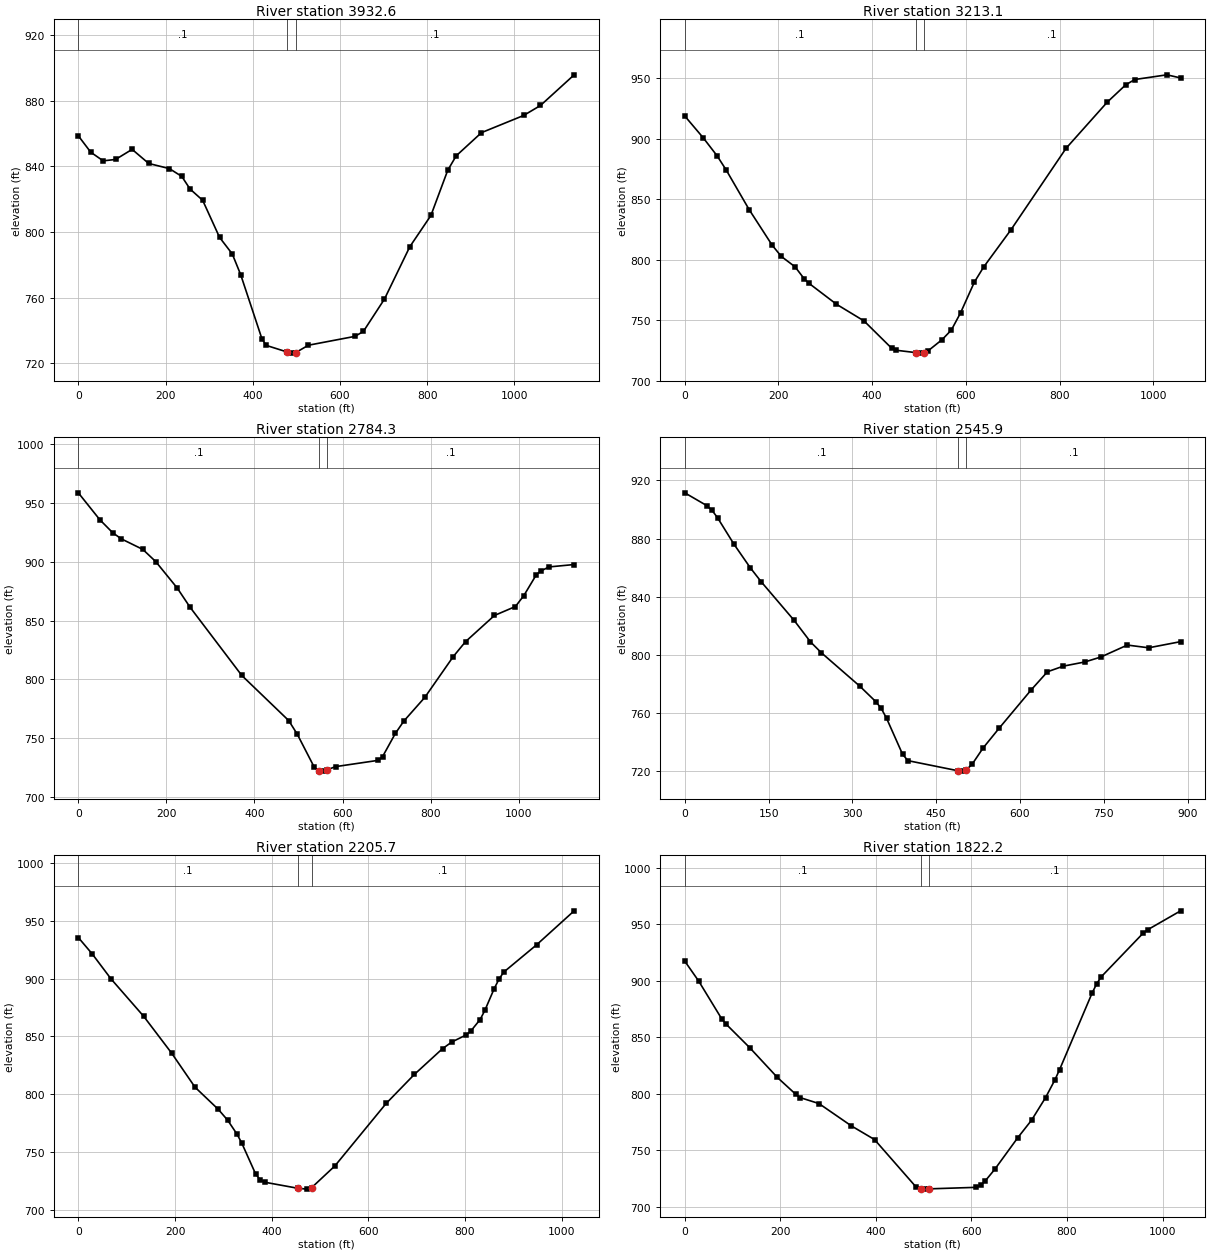
Type RM Length L Ch R = 1 ,3932.6  ,704.3,719.6,733.9
XS GIS Cut Line= 4
     1836638.782      573460.167     1836542.762      573708.034
     1836625.384      574185.903     1836609.753      574572.218
#Sta/Elev= 30
       0  858.66    28.5  848.65      57  843.39    85.4  844.24   123.4  850.39
   161.4   841.8   208.9  838.65   237.3  833.89   256.3  826.18   285.2  819.33
     324  796.68   353.1  786.61   372.5   773.9     421  734.95   430.7  730.83
   479.2  726.75   488.9  726.08   498.6   726.4   527.7   730.9   634.4   736.3
   653.8  739.28   702.3  759.09   760.4     791   808.8  810.06   847.4  837.64
   866.8  846.45   924.8   860.6  1021.4  871.06  1060.1  877.16  1137.4  895.87
#Mann= 3 , 0 , 0
       0      .1       0   479.2    .045       0   498.6      .1       0
Bank Sta=479.2,498.6
XS Rating Curve= 0 ,0
Exp/Cntr=0.3,0.1

Type RM Length L Ch R = 1 ,3213.1  ,428.2,428.8,429.1
XS GIS Cut Line= 4
     1836281.497      573373.078     1836084.989      573565.119
     1835913.046      573917.939     1835933.143       574308.72
#Sta/Elev= 30
       0  918.71    39.2  900.81    68.7  886.02    88.3  874.22   137.4  841.46
   186.4  812.16   206.1   802.8   235.5  794.19   255.1  784.25     265  780.64
   323.8  763.34   382.7  749.53   441.6  727.03   451.4  725.34   492.7  723.42
   500.4  722.97   510.3  723.15   520.1  725.07   549.5  734.17   569.1  742.02
   588.8  756.27   618.2  781.58   637.8  793.92   696.6  824.94     814  892.08
     902   930.2   941.2  944.42   960.7  948.87  1029.2  952.74  1058.6  950.17
#Mann= 3 , 0 , 0
       0      .1       0   492.7    .045       0   510.3      .1       0
Bank Sta=492.7,510.3
XS Rating Curve= 0 ,0
Exp/Cntr=0.3,0.1

Type RM Length L Ch R = 1 ,2784.3  ,219.6,238.4,257.1
XS GIS Cut Line= 5
     1836073.824      573114.046       1835754.5      573321.718
     1835580.323      573667.839     1835609.353      573812.986
     1835515.565      574000.561
#Sta/Elev= 30
       0  958.44    48.8   935.6    78.1  924.53    97.7  919.33   146.5  910.37
   175.8  900.04   224.6  877.58   253.9  861.19   371.2  803.35   477.8  765.02
   497.2  753.46   535.9  725.36   545.6  722.29   555.3  722.08     565  723.24
   584.3   725.9   681.2  731.24   690.9  734.36     720  754.08   739.3   764.6
   786.9   784.7   851.6  819.41   879.4  832.04     945  854.27   992.7  861.88
  1011.7  871.09  1040.3  888.94  1049.9  891.95  1068.9   895.5  1126.1  897.54
#Mann= 3 , 0 , 0
       0      .1       0   545.6    .045       0     565      .1       0
Bank Sta=545.6,565
XS Rating Curve= 0 ,0
Exp/Cntr=0.3,0.1

Type RM Length L Ch R = 1 ,2545.9  ,339.2,340.1,341
XS GIS Cut Line= 4
     1835892.295      573087.765     1835659.501      573297.112
     1835336.269      573389.225     1835239.132      573606.946
#Sta/Elev= 30
       0  911.49    39.1  902.75    48.9  899.37    58.7  894.28      88  876.13
   117.4  859.81     137  850.16   195.7  823.68     225  808.87   244.6  801.34
   313.1  778.44   341.9  767.74   351.5  763.15   361.1  756.35   389.9  731.45
   399.5   727.1   488.6  720.18   495.5  719.89   503.6  720.62   514.7  724.81
     534  735.82   562.8  749.47   620.4  775.98   649.2   788.3   677.8  792.19
   715.9  795.02   744.5  798.41   792.2  806.68   830.4   804.8   887.6  809.04
#Mann= 3 , 0 , 0
       0      .1       0   488.6    .045       0   503.6      .1       0
Bank Sta=488.6,503.6
XS Rating Curve= 0 ,0
Exp/Cntr=0.3,0.1

Type RM Length L Ch R = 1 ,2205.7  ,398.1,383.6,367.8
XS GIS Cut Line= 4
     1835838.702      572818.126     1835643.407      572959.967
     1835259.324      573053.754     1835004.513      573347.593
#Sta/Elev= 30
       0  935.66      29  921.33    67.6  899.85   135.2  867.42   193.1  835.49
   241.4  806.03   289.6  786.81   308.9  777.45   328.2  765.39   337.8   757.9
   366.7  730.93   376.4  725.64     386  723.69   453.5  718.53   472.8  717.74
   482.4  718.93   530.7  737.83   636.7  791.92   695.1  817.07   753.4  839.42
   772.9  845.24     802  851.23   811.8  854.62   831.2  864.65   840.9  872.51
   860.4  891.52   870.1   899.5   879.8  905.64   947.9  929.32  1025.7   958.8
#Mann= 3 , 0 , 0
       0      .1       0   453.5    .045       0   482.4      .1       0
Bank Sta=453.5,482.4
XS Rating Curve= 0 ,0
Exp/Cntr=0.3,0.1

Type RM Length L Ch R = 1 ,1822.2  ,325.3,332.1,338.7
XS GIS Cut Line= 4
     1835732.476      572663.128     1835337.229      572625.166
     1835127.323      572890.898     1834901.787      573091.871
#Sta/Elev= 30
       0   917.5      29  899.94    77.5  866.32    87.2  861.49   135.6  841.09
   193.7  814.66   232.4  799.66   242.1   796.7   280.8  791.53   348.6  771.79
   397.1  759.68   484.1  717.68   493.8  715.91   503.5  715.82   511.4  716.06
   609.9   717.4   619.6  719.39   629.3  723.33   648.6  733.24     697  761.36
     726  776.95   755.2  796.88   774.7  812.51   784.4  821.51   852.6  889.38
   862.4  897.74   872.1  903.89   959.8  942.48   969.6   945.5  1037.8  962.05
#Mann= 3 , 0 , 0
       0      .1       0   493.8    .045       0   511.4      .1       0
Bank Sta=493.8,511.4
XS Rating Curve= 0 ,0
Exp/Cntr=0.3,0.1

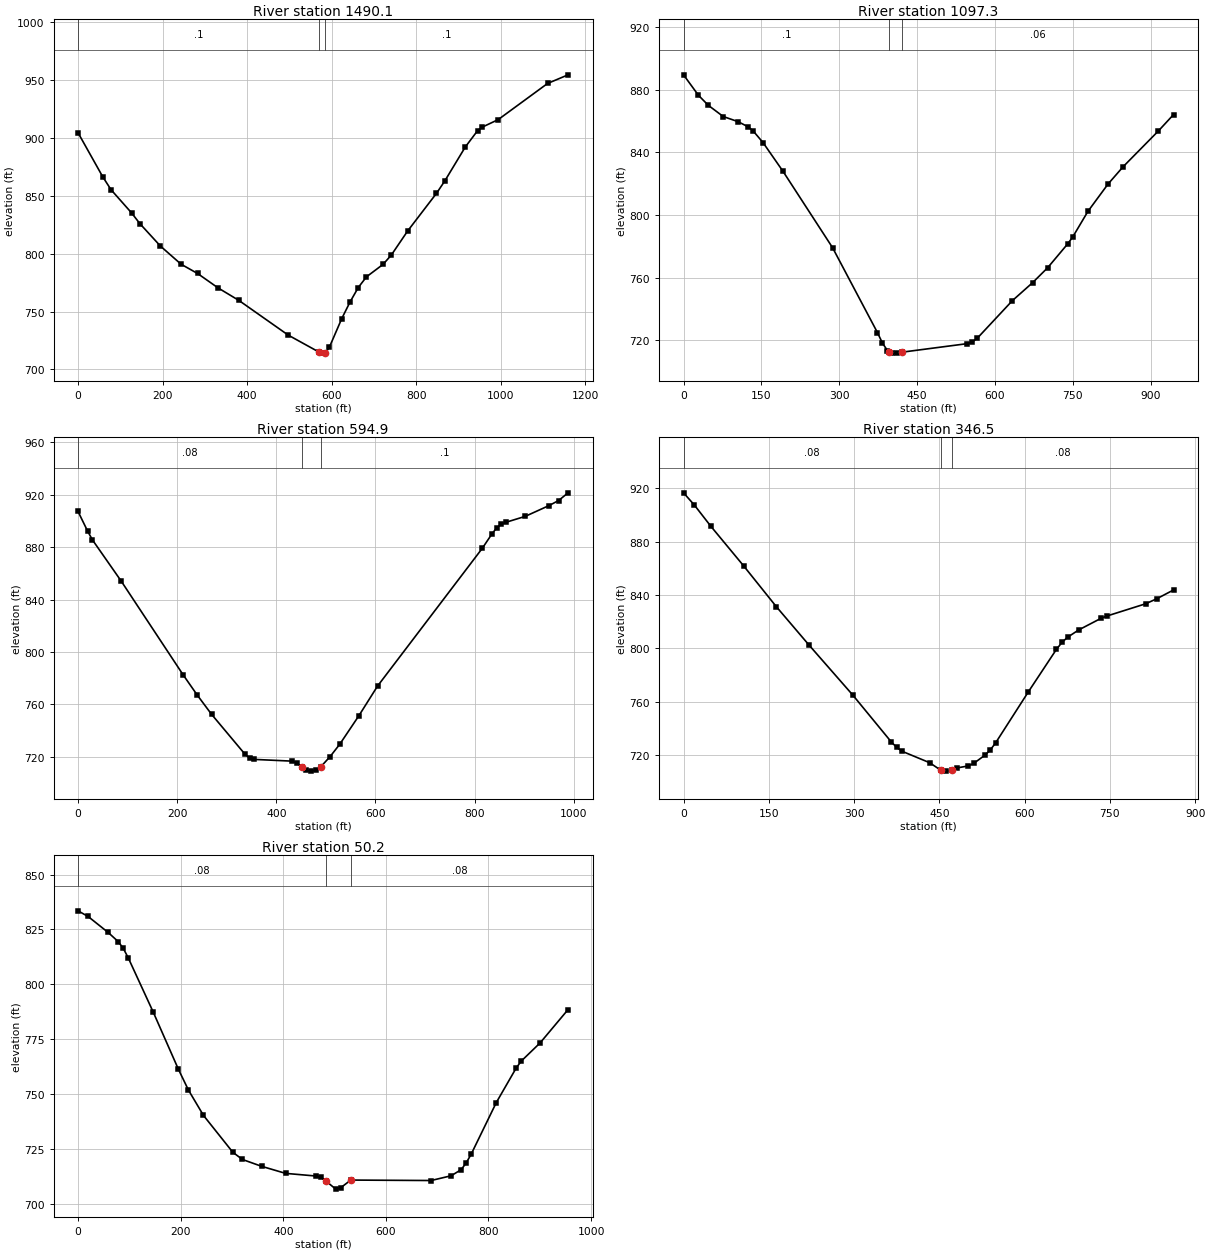
Type RM Length L Ch R = 1 ,1490.1  ,385.2,392.8,399.7
XS GIS Cut Line= 4
     1835524.497      572415.106     1835106.768      572549.899
     1834800.994      572758.993     1834734.003      573102.881
#Sta/Elev= 30
       0  904.49    58.5  866.41      78  855.32   126.8  835.19   146.3  825.97
   195.1  806.54   243.8  790.91   282.9  782.89   331.6  770.39   380.4  759.69
   497.4  729.66  570.37 714.979   575.4  714.09   585.2  714.15   594.9  719.28
   624.2     744   643.6   758.2   663.2  770.78   682.6     780   721.6   790.7
   741.1  798.66   780.1  819.64   848.3  852.15   867.8  862.74   916.4  892.14
   945.6   906.3   955.4  909.13   994.3  915.84  1111.1  947.05  1159.7  954.53
#Mann= 3 , 0 , 0
       0      .1       0  570.37    .045       0   585.2      .1       0
Bank Sta=570.37,585.2
XS Rating Curve= 0 ,0
Exp/Cntr=0.3,0.1

Type RM Length L Ch R = 1 ,1097.3  ,485.7,502.4,518.9
XS GIS Cut Line= 4
      1835276.63      572240.929     1834970.705      572229.764
     1834655.847      572319.085     1834394.581      572486.563
#Sta/Elev= 30
       0  889.57    28.7   876.5    47.8  870.07    76.5  862.93   105.2  859.64
   124.4  856.35   133.9  853.81   153.1  846.29   191.3  828.08     287  779.19
   373.5  724.93   383.1  718.24   392.8  713.43   396.5  712.82   402.4  711.84
   411.5  711.82   421.6  712.46   546.8  717.89   556.4  718.99     566  721.43
   633.4  745.36   672.2  756.79   701.3  766.36   740.1  781.69   749.8  786.12
   778.9  802.38   817.7  819.86   846.8  830.92   914.6  853.73   943.8   864.2
#Mann= 3 , 0 , 0
       0      .1       0   396.5    .045       0   421.6     .06       0
Bank Sta=396.5,421.6
XS Rating Curve= 0 ,0
Exp/Cntr=0.3,0.1

Type RM Length L Ch R = 1 ,594.9   ,251.8,248.4,244.9
XS GIS Cut Line= 4
     1835292.262      571964.033     1835008.666       571910.44
     1834722.838      571776.458     1834361.086      571905.974
#Sta/Elev= 30
       0  907.12    19.2  892.22    28.9  885.54    86.6   854.3   211.6   782.8
   240.5  767.12   269.4  752.46   336.4  722.22     346  719.16   355.6  718.11
   432.1  716.78   441.7  715.28   451.2  712.29   460.8  709.75   470.4  709.17
   479.9  709.93   489.5   712.4   508.6  720.32   527.8  729.59     566   751.1
   604.3  774.08   815.6  879.11   834.8  889.94   844.4  894.59     854  897.37
   863.6  898.93   902.1  903.39   950.1  911.63   969.3  915.44   988.5  921.34
#Mann= 3 , 0 , 0
       0     .08       0   451.2    .045       0   489.5      .1       0
Bank Sta=451.2,489.5
XS Rating Curve= 0 ,0
Exp/Cntr=0.3,0.1

Type RM Length L Ch R = 1 ,346.5   ,313.3,296.4,277.5
XS GIS Cut Line= 4
     1835412.846      571658.107     1835124.784      571662.573
     1834818.858      571573.252     1834566.525      571611.213
#Sta/Elev= 30
       0  916.69    19.2  907.44      48  891.62   105.6  861.95   163.2  831.28
   220.9  802.38   297.8  764.91   365.4  729.81     375  725.66   384.7  722.71
     433  714.18   452.3  708.62   461.9  707.87   471.6  708.75   481.2  710.28
   500.6  711.75   510.2   713.6   529.5  719.62   539.2  723.54   548.8  728.95
   606.8  767.52   655.9  799.21   665.7  804.44   675.5  808.31   695.1  813.81
   734.4  822.53   744.2  824.18   812.9  833.44   832.5  837.22     862  843.82
#Mann= 3 , 0 , 0
       0     .08       0   452.3    .045       0   471.6     .08       0
Bank Sta=452.3,471.6
XS Rating Curve= 0 ,0
Exp/Cntr=0.3,0.1

Type RM Length L Ch R = 1 ,50.2    ,37.4,50.2,64.7
XS GIS Cut Line= 5
     1835479.837      571372.278     1835229.737      571287.423
     1835089.358      571284.008      1834674.85      571482.469
     1834589.437      571513.871
#Sta/Elev= 30
       0  833.49    19.6  830.91    58.7  823.63    78.2  819.49      88  816.46
    97.8  812.09   146.7  787.27   195.6   761.3   215.2   751.8   244.5  740.26
   301.6   723.5   320.3   720.2   357.7  717.08   404.5  713.86   463.2  712.66
     473  712.08   482.8  710.44   502.3  706.68   512.1  707.34   531.6  710.81
   688.1   710.6   727.2  712.77   746.8  715.56   756.5  718.62   766.3  722.62
   815.2  746.12   854.3  761.99   864.1  765.08   900.5  773.28   955.1   788.5
#Mann= 3 , 0 , 0
       0     .08       0   482.8    .045       0   531.6     .08       0
Bank Sta=482.8,531.6
XS Rating Curve= 0 ,0
Exp/Cntr=0.3,0.1

Chan Stop Cuts=-1
Use User Specified Reach Order=0
Composite Channel Slope=5